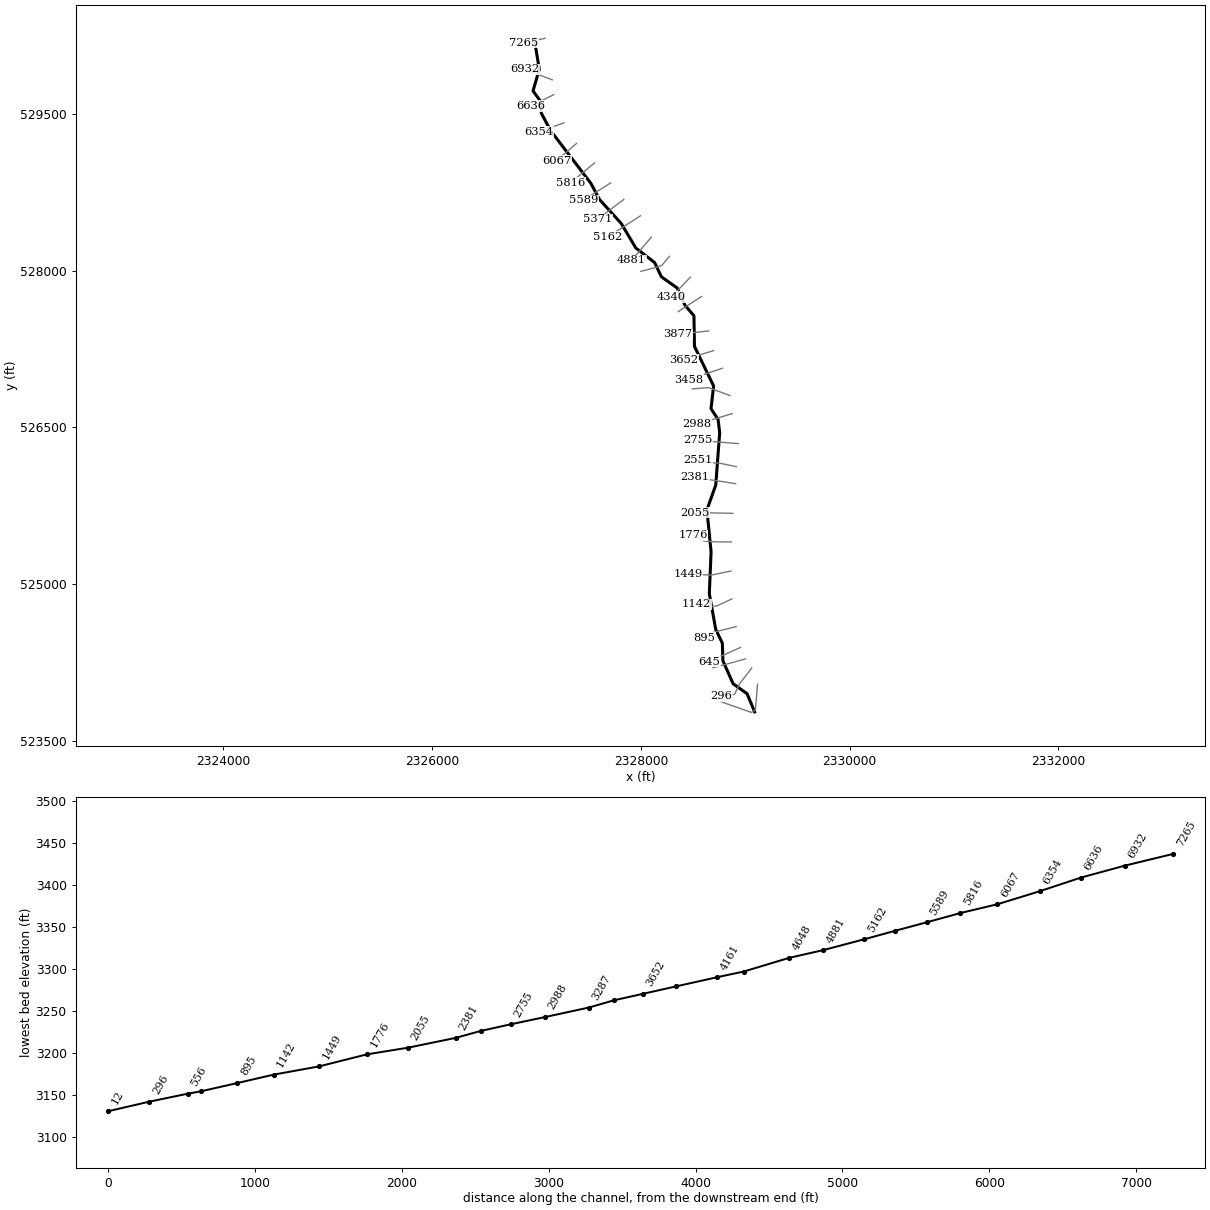
--- BLCKRN.prj (project) ---

Proj Title=BLCKRN
Current Plan=p01
Default Exp/Contr=0,0
English Units
Geom File=g01
Flow File=f01
Plan File=p01
Background Map Layer=Inundation Boundary (01pct Value_0)
BEGIN DESCRIPTION:
----------MODEL BY WOOD PLC 2021----------
Stream Name: Block Run
Flood Zone: Enhanced Approximate
Pocahontas County, WV
HEC-RAS Version: RAS 6.1
Vertical Datum: NAVD88
Projection: NAD 1983 StatePlane West Virginia S FIPS 4702 (US Feet)
Terrain: 1-meter LIDAR (FEMA Region III 3DEP collected 2016-2018)
Land Use: 2019 NLCD
Hydrologic Method:
WV SIR2010-5033 regression equations
Model Notes:
Normal Depth tie in to North Fork
END DESCRIPTION:
DSS Export Rating Curves= 0
DSS Export Rating Curve Sorted= 0
DSS Export Volume Flow Curves= 0
DXF OffsetX= 0
DXF OffsetY= 0
DXF ScaleX= 0
DXF ScaleY= 0

--- BLCKRN.p01 (plan) ---

Plan Title=Floodplain
Program Version=6.10
Short Identifier=Floodplain
Geom File=g01
Flow File=f01
Subcritical Flow
K Sum by GR= 0
Std Step Tol= 0.01
Critical Tol= 0.01
Num of Std Step Trials= 20
Max Error Tol= 0.3
Flow Tol Ratio= 0.001
Split Flow NTrial= 30
Split Flow Tol= 0.02
Split Flow Ratio= 0.02
Log Output Level= 0
Friction Slope Method= 1
Unsteady Friction Slope Method= 2
Unsteady Bridges Friction Slope Method= 1
Parabolic Critical Depth
Global Vel Dist= 0 , 0 , 0
Global Log Level= 0
CheckData=True
Encroach Param=-1 ,0,0, 0
Mapping Interval=1HOUR
Computation Time Step Use Courant=        0
Computation Time Step Use Time Series=    0
Computation Time Step Count To Double=0
Computation Time Step Max Doubling=0
Computation Time Step Max Halving=0
Computation Time Step Residence Courant=0
Run HTab= 0
Run UNet= 0
Run Sediment= 0
Run PostProcess= 0
Run WQNet= 0
Run RASMapper=-1
UNET Theta= 0
UNET Theta Warmup= 0
UNET ZTol= 0
UNET ZSATol= 0
UNET MxIter= 0
UNET Max Iter WO Improvement= 0
UNET MaxInSteps= 0
UNET DtIC= 0
UNET DtMin= 0
UNET MaxCRTS= 0
UNET WFStab= 0
UNET SFStab= 0
UNET WFX= 1
UNET SFX= 1
UNET Gravity=32.174
UNET 1D Methodology=Finite Difference
UNET DSS MLevel= 1
UNET Pardiso=0
UNET DZMax Abort= 0
UNET Use Existing IB Tables= 0
UNET Froude Reduction=False
UNET Froude Limit= 0
UNET Froude Power= 0
UNET D1 Cores= 0
UNET WindReference=Eulerian
UNET WindDragFormulation=Hsu (1988)
UNET D2 Coriolis=0
UNET D2 Cores= 0
UNET D2 Theta= 1
UNET D2 Theta Warmup= 1
UNET D2 Z Tol= 0.01
UNET D2 Volume Tol= 0.01
UNET D2 Max Iterations= 20
UNET D2 Equation= 0
UNET D2 RampUpFraction=0.1
UNET D2 TimeSlices= 1
UNET D2 Turbulence Formulation=Non-Conservative (original)
UNET D2 Eddy Viscosity=0.3
UNET D2 Transverse Eddy Viscosity=0.1
UNET D2 Smagorinsky Mixing=0
UNET D2 BCVolumeCheck=0
UNET D2 Cores=0
UNET D2 SolverType=PARDISO (Direct)
UNET D2 Minimum Iterations= 2147483647
UNET D2 Maximum Iterations= 2147483647
UNET D2 Restart Number= 10
UNET D2 Relaxation Coeff=1.3
UNET D2 SOR Precondition Iterations= 10
UNET D2 ILUT Maximum Fill= 8
UNET D2 ILUT Tolerance=1E-08
UNET D1D2 MaxIter= 0
UNET D1D2 ZTol=0.01
UNET D1D2 QTol=0.1
UNET D1D2 MinQTol=1
Write IC File= 0
Write IC File at Fixed DateTime=0
Write IC File at Sim End=0
Echo Input=False
Echo Parameters=False
Echo Output=False
Write Detailed= 0
HDF Write Warmup=0
HDF Write Time Slices=0
HDF Flush=0
HDF Compression= 1
HDF Chunk Size= 1
HDF Spatial Parts= 1
HDF Use Max Rows=0
HDF Fixed Rows= 1
Calibration Method= 0
Calibration Iterations= 20
Calibration Max Change=0.05
Calibration Tolerance=0.2
Calibration Maximum=1.5
Calibration Minimum=0.5
Calibration Optimization Method= 1
WQ AD Non Conservative
WQ ULTIMATE=-1
WQ Max Comp Step=1HOUR
WQ Output Interval=15MIN
WQ Output Selected Increments= 0
WQ Output face flow=0
WQ Output face velocity=0
WQ Output face area=0
WQ Output face dispersion=0
WQ Output cell volume=0
WQ Output cell surface area=0
WQ Output cell continuity=0
WQ Output cumulative cell continuity=0
WQ Output face conc=0
WQ Output face dconc_dx=0
WQ Output face courant=0
WQ Output face peclet=0
WQ Output face adv mass=0
WQ Output face disp mass=0
WQ Output cell mass=0
WQ Output cell source sink temp=0
WQ Output nsm pathways=0
WQ Output nsm derived pathways=0
WQ Create Restart=0
WQ Fixed Restart=0
WQ System Summary=0
WQ Write To DSS=0
Sorting and Armoring Iterations= 10
XS Update Threshold= 0.02
Bed Roughness Predictor= 0
Hydraulics Update Threshold= 0.02
Energy Slope Method= 1
Volume Change Method= 1
Sediment Retention Method= 0
Sediment TS Multiplier= 1
Warm Up Method= 0
XS Weighting Method= 0
Number of US Weighted Cross Sections= 1
Number of DS Weighted Cross Sections= 1
Upstream XS Weight=0
Main XS Weight=1
Downstream XS Weight=0
Number of DS XS's Weighted with US Boundary= 1
Upstream Boundary Weight= 1
Weight of XSs Associated with US Boundary= 0
Number of US XS's Weighted with DS Boundary= 1
Downstream Boundary Weight= 0.5
Weight of XSs Associated with DS Boundary= 0.5
Percentile Method= 0
Sediment Output Level= 3
Mass or Volume Output= 0
Output Increment Type= 1
Profile and TS Output Increment= 1
Transport Output Increment 1
XS Output Flag= 0
XS Output Increment= 10
Read HDF5 Sediment Hotstart= 0
Sediment Hotstart Type= 0
Write Gradation File= 0
Read Gradation Hotstart= 0
Write HDF5 File= 1
Write Binary Output= 1
Write DSS Sediment File= 0
DSS Sediment Output Type= 1
SV Curve= 0
Specific Gage Flag= 0
Subcell Erosion Methods= 0
Subcell Deposition Methods= 0
Advection Scheme= 1
Matrix Solver= 0
Implicit Weighting Factor= 1
Maximum Outer Loop Convergence Iterations= 5
Convergence Maximum Absolute= 0.001
Convergence RMSE= 0.0001
Grain Fractions Max Abs Error= 0.001
Max Subgrid Regions= 1
Max Subgrid Length Scale= 3.402823E+38
Initial Layer Thickness= 3.402823E+38
Min Layer Thickness= 3.402823E+38
Max Layer Thickness= 3.402823E+38
Number of Layers= 5

--- BLCKRN.f01 (steady flow) ---

Flow Title=Flow
Program Version=6.10
Number of Profiles= 6
Profile Names=01pct,10pct,04pct,02pct,0_2pct,01plus
River Rch & RM=BLCKRN,Main            ,7265
     623     330     439     528     869     922
River Rch & RM=BLCKRN,Main            ,4161
     700     373     494     594     974    1040
Boundary for River Rch & Prof#=BLCKRN,Main            , 1
Up Type= 0
Dn Type= 3
Dn Slope=0.03743
Boundary for River Rch & Prof#=BLCKRN,Main            , 2
Up Type= 0
Dn Type= 3
Dn Slope=0.03743
Boundary for River Rch & Prof#=BLCKRN,Main            , 3
Up Type= 0
Dn Type= 3
Dn Slope=0.03743
Boundary for River Rch & Prof#=BLCKRN,Main            , 4
Up Type= 0
Dn Type= 3
Dn Slope=0.03743
Boundary for River Rch & Prof#=BLCKRN,Main            , 5
Up Type= 0
Dn Type= 3
Dn Slope=0.03743
Boundary for River Rch & Prof#=BLCKRN,Main            , 6
Up Type= 0
Dn Type= 3
Dn Slope=0.03743
DSS Import GetInterval= 0
DSS Import GetPeak= 0
DSS Import FillOption= 0

--- BLCKRN.g01 (geometry) ---

Geom Title=Geometry
Program Version=6.10

River Reach=BLCKRN          ,Main
Reach XY= 30
     2326980.818      530205.584      2327026.99      529928.297
     2326967.103      529721.348     2327045.542      529612.311
     2327045.623      529509.349      2327134.88      529341.834
     2327520.992      528836.626     2327604.171      528681.193
     2327813.315      528450.364       2327951.9      528217.039
     2328131.885       528078.16      2328197.07      527941.634
      2328347.38       527834.89     2328422.727      527669.265
     2328508.492       527568.57     2328513.284       527276.34
     2328696.948      526896.417     2328671.962      526679.252
     2328739.547      526576.598     2328755.019       526449.82
     2328717.361      525948.158     2328632.618      525710.682
     2328672.648      525308.425     2328655.714      524908.848
      2328717.25      524566.223     2328780.581      524434.877
     2328786.076      524266.059     2328883.581      524046.666
     2329017.458      523950.972     2329090.049      523777.266

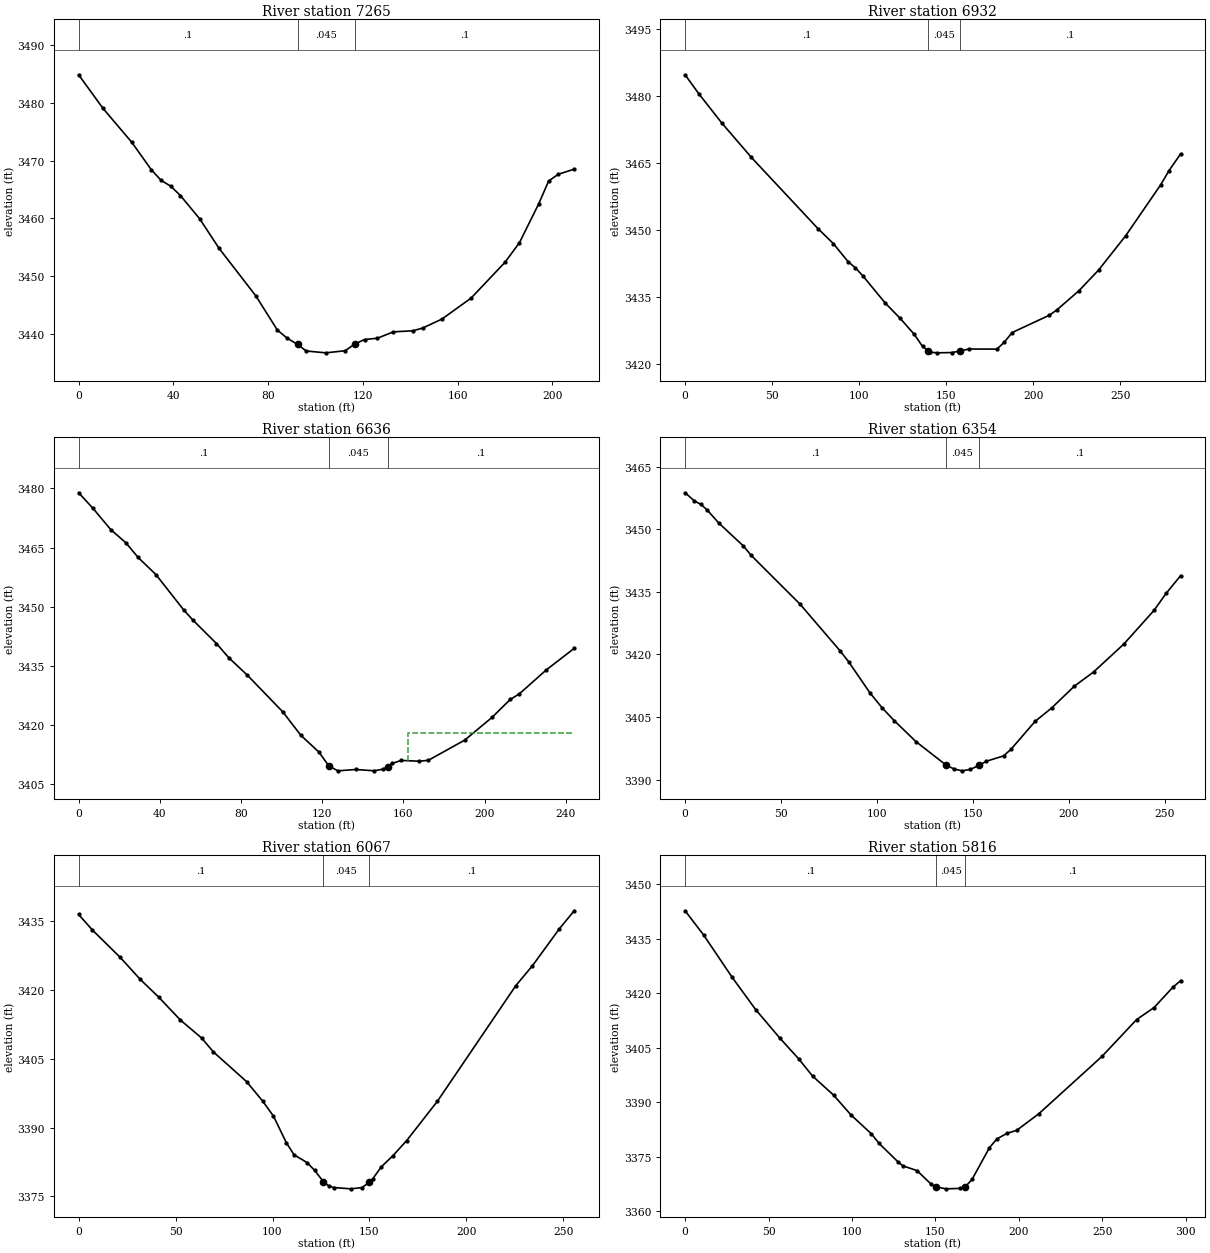
Type RM Length L Ch R = 1 ,7265    ,332.8,332.8,332.8
XS GIS Cut Line= 2
2327082.17783047530224.8076659482326877.57425746530181.075604541
#Sta/Elev= 30
       0 3484.91    10.2 3479.13    22.5 3473.17    30.7 3468.44    34.8 3466.61
    38.9 3465.59      43 3463.96    51.1 3459.94    59.3 3454.81    74.8 3446.58
    83.9 3440.65    87.9 3439.28    92.4 3438.16    96.1 3437.02   104.3  3436.7
   112.5 3437.06   116.6 3438.23   120.7 3439.01   126.1 3439.23   132.9 3440.34
   141.1 3440.52   145.2 3440.99   153.4 3442.56   165.7  3446.2     180  3452.4
   186.1  3455.8   194.3 3462.59   198.4 3466.48   202.5 3467.66   209.2 3468.55
#Mann= 3 ,0,0
       0      .1       0    92.4    .045       0   116.6      .1       0
Bank Sta=92.4,116.6
XS Rating Curve= 0 ,0
Exp/Cntr(USF)=0,0
Exp/Cntr=0.3,0.1

Type RM Length L Ch R = 1 ,6932    ,279.1,296.2,305.8
XS GIS Cut Line= 2
2327151.77963049529826.7457236452326885.51403217529927.256578641
#Sta/Elev= 30
       0 3484.85     8.1 3480.48      21 3474.08    38.1 3466.32    76.5  3450.3
    85.1 3447.04    93.6 3442.98    97.8 3441.58   102.2 3439.74     115 3433.67
   123.6 3430.24   131.5 3426.73   136.4 3423.97   139.4 3423.06   140.7 3422.69
   144.9 3422.54   153.5 3422.61   157.8 3422.95     163  3423.4   179.1 3423.37
   183.4 3424.95   187.8 3427.08   209.1 3430.95   213.4 3432.12   226.2 3436.46
   237.5  3441.1     253 3448.76   273.2 3460.23   277.8  3463.3   284.6 3467.13
#Mann= 3 ,-1,0
       0      .1       0   139.4    .045       0   157.8      .1       0
Bank Sta=139.4,157.8
XS Rating Curve= 0 ,0
Exp/Cntr(USF)=0,0
Exp/Cntr=0.3,0.1

Type RM Length L Ch R = 1 ,6636    ,283.6,281.8,279
XS GIS Cut Line= 2
 2327166.4346919529685.9665075122326947.93108042529577.117844965
#Sta/Elev= 30
       0  3478.9       7    3475    15.9 3469.52    23.2 3466.27    29.3 3462.52
    38.1 3458.16    51.7 3449.25    56.2 3446.69    67.9  3440.7      74 3437.08
      83 3432.74   100.7 3423.31   109.4 3417.48   118.4 3413.17   123.2 3409.72
   127.7 3408.44   136.5 3408.78   145.5 3408.46     150 3408.86   152.23409.487
   154.5 3410.32   158.9 3411.08   167.9 3410.87   172.3 3411.12   190.2 3416.23
   203.6 3421.97   212.6 3426.52   217.1 3427.95   230.4 3434.03   244.1 3439.47
#Mann= 3 ,-1,0
       0      .1       0   123.2    .045       0   152.2      .1       0
#XS Ineff= 2 , 0
                          162.38         3418.15
Permanent Ineff=
       F       F
Bank Sta=123.2,152.2
XS Rating Curve= 0 ,0
Exp/Cntr(USF)=0,0
Exp/Cntr=0.3,0.1

Type RM Length L Ch R = 1 ,6354    ,281,287.2,292.4
XS GIS Cut Line= 2
2327264.80163139529415.0542807292327020.49685545529331.200496248
#Sta/Elev= 30
       0 3458.73     4.9 3456.76     8.3 3455.93    11.4 3454.66    17.6 3451.46
    30.3 3446.02    34.5 3443.71    59.9 3432.05    80.7  3420.9    85.2 3418.27
    96.4 3410.75   102.7  3407.2     109 3404.14   120.3 3399.12     136 3393.49
   140.2 3392.54   144.5  3392.1   148.7 3392.44   153.1  3393.4   157.1 3394.41
     166 3395.68   169.8 3397.23   182.5 3403.98     191 3407.14   202.9 3412.39
   212.9 3415.78   228.7 3422.49   244.4 3430.53   250.7 3434.61   258.3 3438.87
#Mann= 3 ,-1,0
       0      .1       0     136    .045       0   153.1      .1       0
Bank Sta=136,153.1
XS Rating Curve= 0 ,0
Exp/Cntr(USF)=0,0
Exp/Cntr=0.3,0.1

Type RM Length L Ch R = 1 ,6067    ,251.6,251.2,250.7
XS GIS Cut Line= 2
2327384.27911726529219.1532325522327190.72614316529052.144666332
#Sta/Elev= 30
       0 3436.46     7.1 3433.08    21.4 3427.13    31.8 3422.31    41.2 3418.48
    52.5 3413.45    63.5 3409.51    69.5  3406.5    86.6 3400.04    94.9 3395.79
   100.5  3392.5   107.1 3386.74   111.1 3384.07   117.8 3382.38   121.7 3380.69
   126.3 3378.18   129.1 3377.27   131.6 3376.94   140.4 3376.65   146.1 3376.92
     150 3378.08   151.8 3378.88   156.1 3381.44   162.2 3383.91   169.2 3387.17
   185.1 3395.77   225.5 3420.95     234 3425.25   247.9 3433.31   255.6 3437.27
#Mann= 3 ,-1,0
       0      .1       0   126.3    .045       0     150      .1       0
Bank Sta=126.3,150
XS Rating Curve= 0 ,0
Exp/Cntr(USF)=0,0
Exp/Cntr=0.3,0.1

Type RM Length L Ch R = 1 ,5816    ,228.4,227,224.7
XS GIS Cut Line= 2
2327556.81776845529032.2363604252327327.87225052528843.107454308
#Sta/Elev= 30
       0 3442.67    11.1 3436.02    28.2 3424.38    42.3  3415.5    56.6 3407.76
      68    3402    76.5 3397.17      89 3391.99    99.4 3386.55   111.6 3381.37
   116.3 3378.69   127.6 3373.64   130.5 3372.55     139 3371.23   147.5 3367.49
   150.4 3366.73   156.5 3366.22   164.6 3366.34   167.9 3366.78     172 3368.82
   182.4 3377.53   186.9 3379.96     193 3381.49   198.7 3382.29   212.1  3386.9
   249.9 3402.65   270.6 3412.75   281.1 3416.07   292.4 3421.68     297 3423.45
#Mann= 3 ,-1,0
       0      .1       0   150.4    .045       0   167.9      .1       0
Bank Sta=150.4,167.9
XS Rating Curve= 0 ,0
Exp/Cntr(USF)=0,0
Exp/Cntr=0.3,0.1

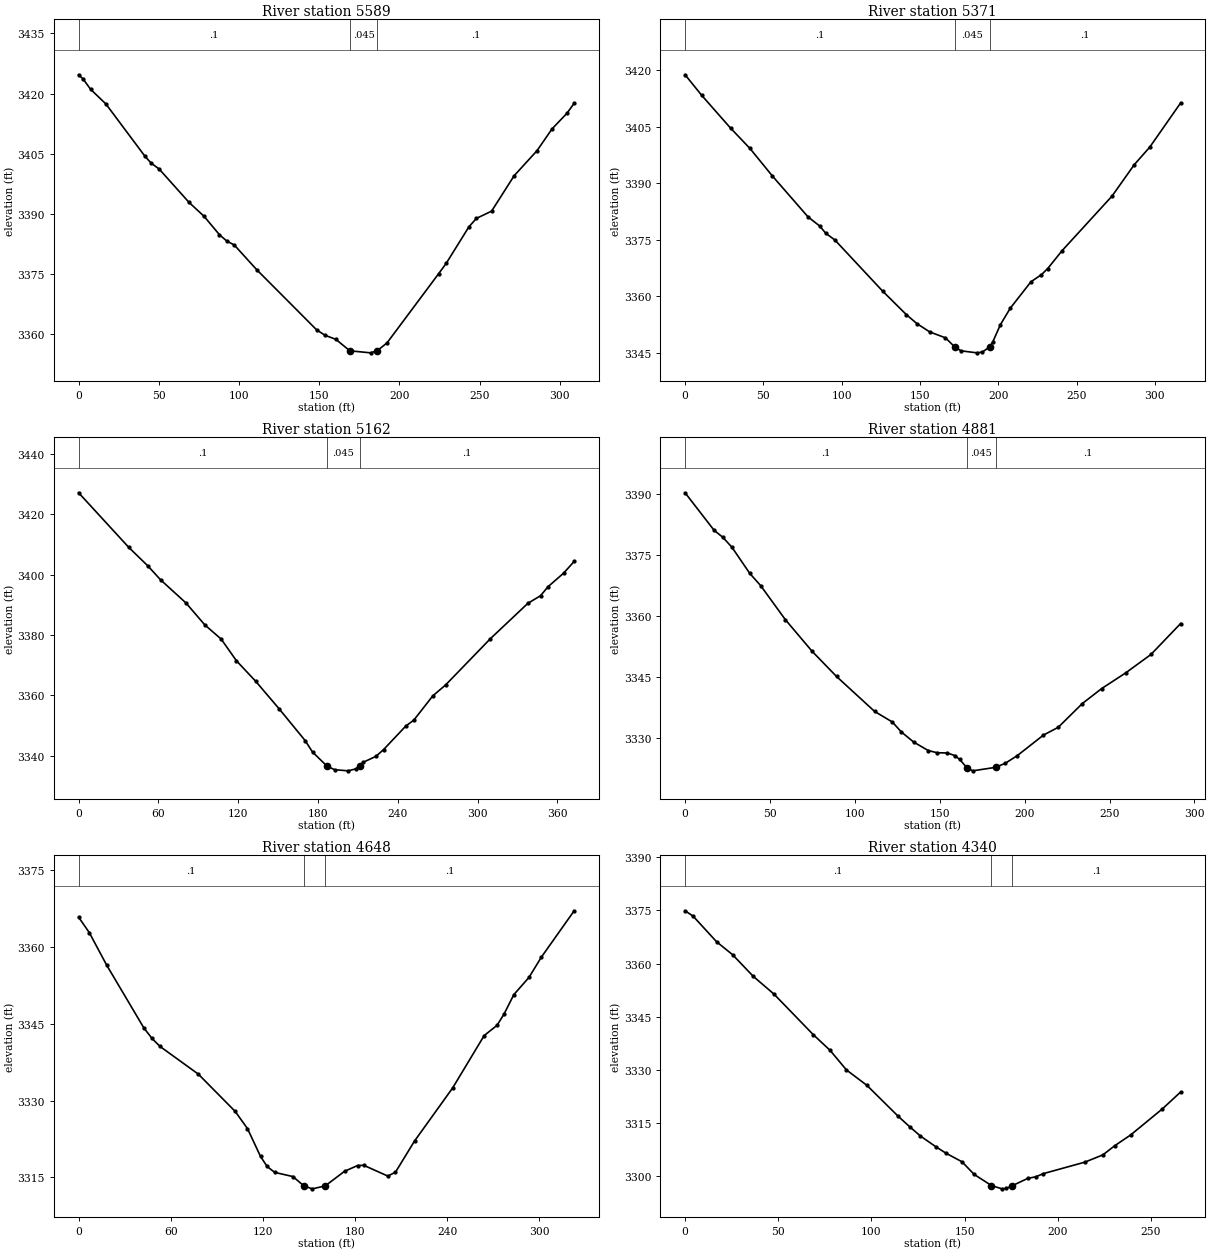
Type RM Length L Ch R = 1 ,5589    ,216.6,217.6,219
XS GIS Cut Line= 2
2327710.55413073528839.7894033232327448.42810296528676.098888087
#Sta/Elev= 30
       0 3424.68     2.8 3423.62     7.5 3421.04      17  3417.4    41.4 3404.32
    45.2 3402.64    50.2 3401.16    68.8 3392.85    78.3 3389.32    87.8 3384.76
    92.4 3383.18    97.1 3382.18     111 3376.05   148.4 3361.02   153.7 3359.65
   160.4 3358.65   169.1 3355.79     182 3355.28   186.2 3355.81   192.3 3357.76
   224.5 3375.04   229.2 3377.61   243.3 3386.69     248 3388.83   257.5 3390.64
   271.6  3399.5   285.8 3405.72   295.2 3411.17   304.6 3415.12     309 3417.58
#Mann= 3 ,-1,0
       0      .1       0   169.1    .045       0   186.2      .1       0
Bank Sta=169.1,186.2
XS Rating Curve= 0 ,0
Exp/Cntr(USF)=0,0
Exp/Cntr=0.3,0.1

Type RM Length L Ch R = 1 ,5371    ,210.3,209,207.5
XS GIS Cut Line= 2
2327836.64006814528682.7349900562327584.46819332 528491.39404995
#Sta/Elev= 30
       0 3418.81    10.6 3413.36      29 3404.68    41.4 3399.28    55.8 3391.94
    78.5 3381.12    85.9 3378.71    89.9 3376.75    95.7 3374.97   126.1 3361.45
   141.3 3355.19   148.2 3352.76   156.2 3350.61   166.3 3349.03   172.43346.547
   176.3 3345.58   186.4 3345.05   189.9 3345.26   194.5 3346.62   196.4 3347.85
   201.4 3352.53   207.7  3356.9   220.9  3363.9   227.6 3365.79   231.6 3367.41
   240.8 3372.16   272.7 3386.64   286.9 3394.97   296.8 3399.63   316.5 3411.34
#Mann= 3 ,-1,0
       0      .1       0   172.4    .045       0   194.5      .1       0
Bank Sta=172.4,194.5
XS Rating Curve= 0 ,0
Exp/Cntr(USF)=0,0
Exp/Cntr=0.3,0.1

Type RM Length L Ch R = 1 ,5162    ,276.9,281.3,284.8
XS GIS Cut Line= 2
 2327995.9065154 528525.680576792327682.90370586528323.279466734
#Sta/Elev= 30
       0 3427.07    37.8 3408.95    52.1 3402.84    61.6 3398.26    80.7  3390.6
    94.9 3383.32   107.2 3378.63   118.7 3371.43   133.1 3364.68   150.6 3355.63
   170.4 3344.99   175.9 3341.22   186.83336.557   192.5 3335.37   202.7 3334.99
   208.5 3335.65   211.3 3336.68   214.2 3337.86   223.6 3339.79   229.3    3342
   246.1 3349.84   252.1 3351.78   266.4 3359.83     276 3363.43   309.7 3378.76
   337.9 3390.47   347.4 3392.98   353.1 3395.99   364.7 3400.43   372.7 3404.34
#Mann= 3 ,-1,0
       0      .1       0   186.8    .045       0   211.3      .1       0
Bank Sta=186.8,211.3
XS Rating Curve= 0 ,0
Exp/Cntr(USF)=0,0
Exp/Cntr=0.3,0.1

Type RM Length L Ch R = 1 ,4881    ,240.9,232.6,228
XS GIS Cut Line= 2
2328100.97812991 528322.173449742327911.84922379528099.864033778
#Sta/Elev= 30
       0 3390.41    17.1 3381.17    22.3 3379.43    27.6    3377    38.1 3370.57
    44.5 3367.57    59.1 3359.17    74.8 3351.41    89.2 3345.21   111.6 3336.62
   122.1    3334   127.3 3331.59   134.6 3329.08   143.2 3326.99   148.4 3326.45
   154.5 3326.38   158.9 3325.74   161.7 3324.81   165.9 3322.81   169.4 3321.99
   182.9 3322.85   188.6 3323.85   195.6 3325.71   211.1 3330.79   219.8  3332.7
     234 3338.55   245.3 3342.21   259.5 3346.08   274.4 3350.62   291.9 3358.24
#Mann= 3 ,-1,0
       0      .1       0   165.9    .045       0   182.9      .1       0
Bank Sta=165.9,182.9
XS Rating Curve= 0 ,0
Exp/Cntr(USF)=0,0
Exp/Cntr=0.3,0.1

Type RM Length L Ch R = 1 ,4648    ,300.6,308.5,312.4
XS GIS Cut Line= 4
2328273.15226966528137.9558247612328200.58649463528050.151236973
 2328138.1799281528029.8328199642327999.40517897527994.091204494
#Sta/Elev= 30
       0 3365.86     6.9 3362.87    18.3 3356.47    42.5  3344.2    47.7 3342.19
    52.9 3340.61      78 3335.16     102 3327.87     110 3324.51   118.5 3319.06
   122.8  3317.1   127.7 3315.95   139.6 3315.13   146.7 3313.31   152.2 3312.73
   160.6  3313.3   173.2 3316.16   181.7 3317.29   185.7 3317.34   201.4 3315.23
   206.4 3315.99   218.8 3322.08   243.6 3332.45   264.2 3342.72   272.5  3344.7
     277 3346.85   283.5 3350.72   293.4  3354.1   301.4 3358.04   322.8 3367.12
#Mann= 3 ,-1,0
       0      .1       0   146.7    .045       0   160.6      .1       0
Bank Sta=146.7,160.6
XS Rating Curve= 0 ,0
Exp/Cntr(USF)=0,0
Exp/Cntr=0.3,0.1

Type RM Length L Ch R = 1 ,4340    ,179.2,178.4,176.2
XS GIS Cut Line= 2
2328475.91789116527939.4915695262328291.21305302527748.150629419
#Sta/Elev= 30
       0 3374.91     4.3 3373.39    16.9 3366.17    25.5 3362.51    36.6  3356.4
    47.7  3351.4    68.7    3340    77.8 3335.53    86.6    3330    97.6 3325.64
   114.4  3316.9   120.6 3313.94   126.3 3311.35   134.4 3308.39   140.1 3306.48
   148.6 3304.09   155.1 3300.53   164.4 3297.39     170 3296.46   172.4 3296.59
   175.6 3297.35   183.9 3299.42   188.2 3299.86   192.2 3300.75   214.5 3303.99
   224.2 3306.05   230.6 3308.65   239.1 3311.67   256.1 3319.02   265.9 3323.78
#Mann= 3 ,-1,0
       0      .1       0   164.4    .045       0   175.6      .1       0
Bank Sta=164.4,175.6
XS Rating Curve= 0 ,0
Exp/Cntr(USF)=0,0
Exp/Cntr=0.3,0.1

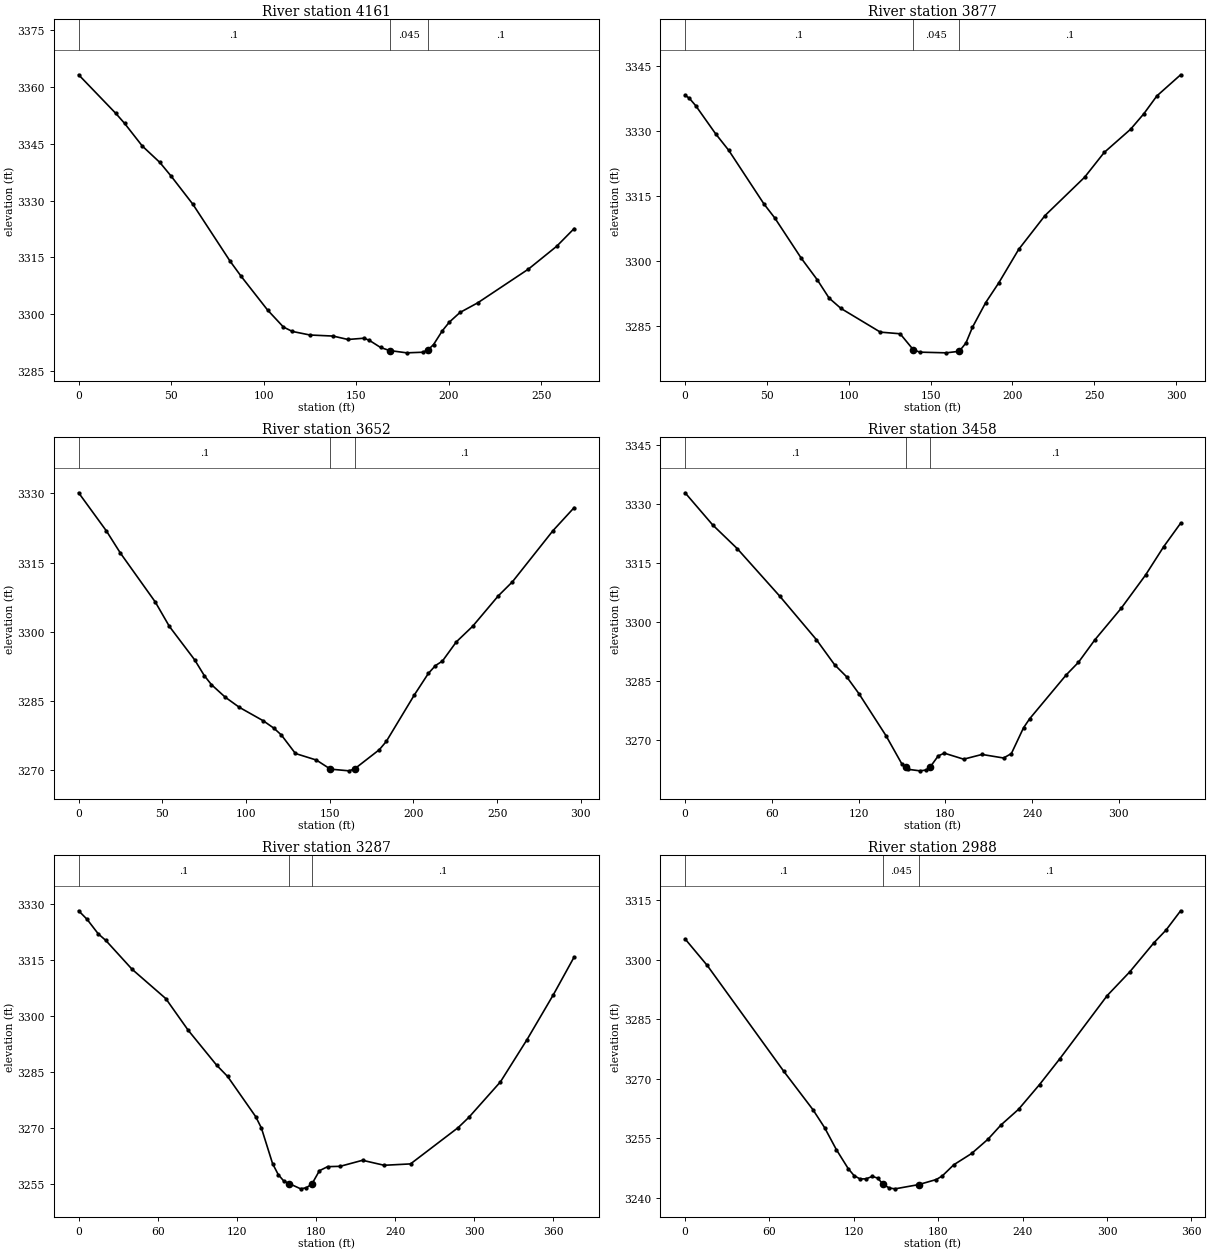
Type RM Length L Ch R = 1 ,4161    ,291.5,284.7,276.8
XS GIS Cut Line= 2
2328580.98950567527753.6807143942328356.46805572527607.686471075
#Sta/Elev= 30
       0 3363.23    20.1 3353.03    24.8 3350.42    34.4 3344.42    43.9 3340.08
    50.1  3336.4    61.7 3329.07    81.9 3313.98    87.7  3310.1   102.1 3301.12
   110.7 3296.61   115.5 3295.46     125 3294.52   137.5 3294.24   145.5 3293.34
   154.2 3293.67   157.1 3293.11   163.2 3291.22     168 3290.42   177.3 3289.81
     186 3289.97   188.9 3290.64   191.8 3291.99   196.6 3295.67   200.4 3297.95
   206.1 3300.47   215.7 3303.02   243.1 3311.93   258.3 3317.93   267.8 3322.63
#Mann= 3 ,-1,0
       0      .1       0     168    .045       0   188.9      .1       0
Bank Sta=168,188.9
XS Rating Curve= 0 ,0
Exp/Cntr(USF)=0,0
Exp/Cntr=0.3,0.1

Type RM Length L Ch R = 1 ,3877    ,220.9,224.4,226.7
XS GIS Cut Line= 2
2328650.66857634527424.0876499322328349.83195375527389.801123092
#Sta/Elev= 30
       0 3338.24     2.5 3337.61     6.5 3335.85    18.6 3329.38    26.7 3325.51
    48.2 3313.12    54.8 3309.89      71 3300.57    80.8 3295.57      88 3291.36
    95.2 3288.98   119.3 3283.49   131.4 3283.11   139.4 3279.44   143.4 3278.86
   159.5  3278.7   167.6 3279.06   167.6  3279.1   171.6 3280.97   175.6 3284.62
   183.7 3290.33   191.7  3294.9   203.8  3302.6   219.9 3310.44   244.1  3319.3
   256.1 3325.04   272.2  3330.4   280.3 3333.98   288.3 3338.12   302.8    3343
#Mann= 3 ,-1,0
       0      .1       0   139.4    .045       0   167.6      .1       0
Bank Sta=139.4,167.6
XS Rating Curve= 0 ,0
Exp/Cntr(USF)=0,0
Exp/Cntr=0.3,0.1

Type RM Length L Ch R = 1 ,3652    ,194.1,194.8,194.3
XS GIS Cut Line= 2
2328696.01527313527234.9587438152328412.87492245527148.689418218
#Sta/Elev= 30
       0 3330.15    16.6 3321.87    24.9  3317.1    45.8 3306.46    54.2 3301.18
    69.3 3293.93    75.1 3290.49    79.3 3288.56    87.6 3285.82      96 3283.63
   110.3 3280.71   116.7 3279.09   121.1 3277.63   129.5 3273.62     142  3272.2
   150.4 3270.23   161.5 3269.86   164.8 3270.27   179.6 3274.44   183.8 3276.25
   200.5  3286.3   208.9 3290.98   213.1 3292.67   217.3 3293.66   225.6 3297.82
   235.3 3301.18   250.7 3307.81   259.1 3310.84   283.3 3321.92     296 3326.94
#Mann= 3 ,-1,0
       0      .1       0   150.4    .045       0   164.8      .1       0
Bank Sta=150.4,164.8
XS Rating Curve= 0 ,0
Exp/Cntr(USF)=0,0
Exp/Cntr=0.3,0.1

Type RM Length L Ch R = 1 ,3458    ,181,170.4,162.8
XS GIS Cut Line= 2
2328782.28459873  527066.84416062328457.11560225526958.454495106
#Sta/Elev= 30
       0 3332.85    19.1 3324.68      36  3318.7    65.5 3306.59    90.8 3295.57
   103.4  3289.2   111.8 3286.11   120.3 3281.82     139 3271.16   149.8  3264.1
   152.5 3263.16     154 3262.65   162.4 3262.25   166.7 3262.45   169.7 3263.31
   175.1 3266.04   179.3 3266.74   192.7 3265.21   205.4 3266.41   220.3 3265.51
   225.7 3266.63   234.1 3273.17   238.3 3275.45   263.6 3286.59   272.1  3289.8
   283.5 3295.53   301.6 3303.49   318.5 3311.95   331.1 3319.18   342.8 3325.13
#Mann= 3 ,-1,0
       0      .1       0   152.5    .045       0   169.7      .1       0
Bank Sta=152.5,169.7
XS Rating Curve= 0 ,0
Exp/Cntr(USF)=0,0
Exp/Cntr=0.3,0.1

Type RM Length L Ch R = 1 ,3287    ,289.5,299.2,307.9
XS GIS Cut Line= 3
2328854.17570339526804.7181328242328647.35052536526881.033305467
2328492.50814608526868.867118524
#Sta/Elev= 30
       0 3328.23     6.4 3325.94    14.9 3322.03    20.6 3320.28    40.5 3312.55
    66.1 3304.67    83.1 3296.17   104.7 3286.79     113 3283.77   134.3 3272.99
   138.6 3269.95   147.1 3260.38   151.4 3257.44   155.6 3255.72   159.9 3255.01
   168.4 3253.63   172.7 3253.93   176.9 3254.92   182.6 3258.49   188.8 3259.58
   198.3 3259.67   215.3 3261.29   231.7 3259.95   251.7 3260.32   287.8 3270.05
   295.9  3272.8   319.9 3282.34     340 3293.64   360.1 3305.76   375.8 3315.84
#Mann= 3 ,-1,0
       0      .1       0   159.9    .045       0   176.9      .1       0
Bank Sta=159.9,176.9
XS Rating Curve= 0 ,0
Exp/Cntr(USF)=0,0
Exp/Cntr=0.3,0.1

Type RM Length L Ch R = 1 ,2988    ,238.2,232.8,226.8
XS GIS Cut Line= 2
2328875.19002629526632.1794816292328537.85484287526530.425918104
#Sta/Elev= 30
       0 3305.26    15.7  3298.6      70 3271.97    90.9 3262.22    99.2 3257.68
   107.5 3252.18     116 3247.35   120.1 3245.62   124.3 3244.78   128.5 3244.78
   133.2 3245.41   136.8 3244.98     141 3243.37   145.2 3242.47   149.3 3242.27
   166.1 3243.34   178.6 3244.62   182.8 3245.51     191 3248.33   203.7 3251.18
   215.4  3254.8   224.6 3258.38   237.1 3262.33     252 3268.56   266.4 3275.06
   300.1 3290.99   316.2 3296.99   333.2 3304.25   341.9 3307.49   352.3 3312.36
#Mann= 3 ,-1,0
       0      .1       0     141    .045       0   166.1      .1       0
Bank Sta=141,166.1
XS Rating Curve= 0 ,0
Exp/Cntr(USF)=0,0
Exp/Cntr=0.3,0.1

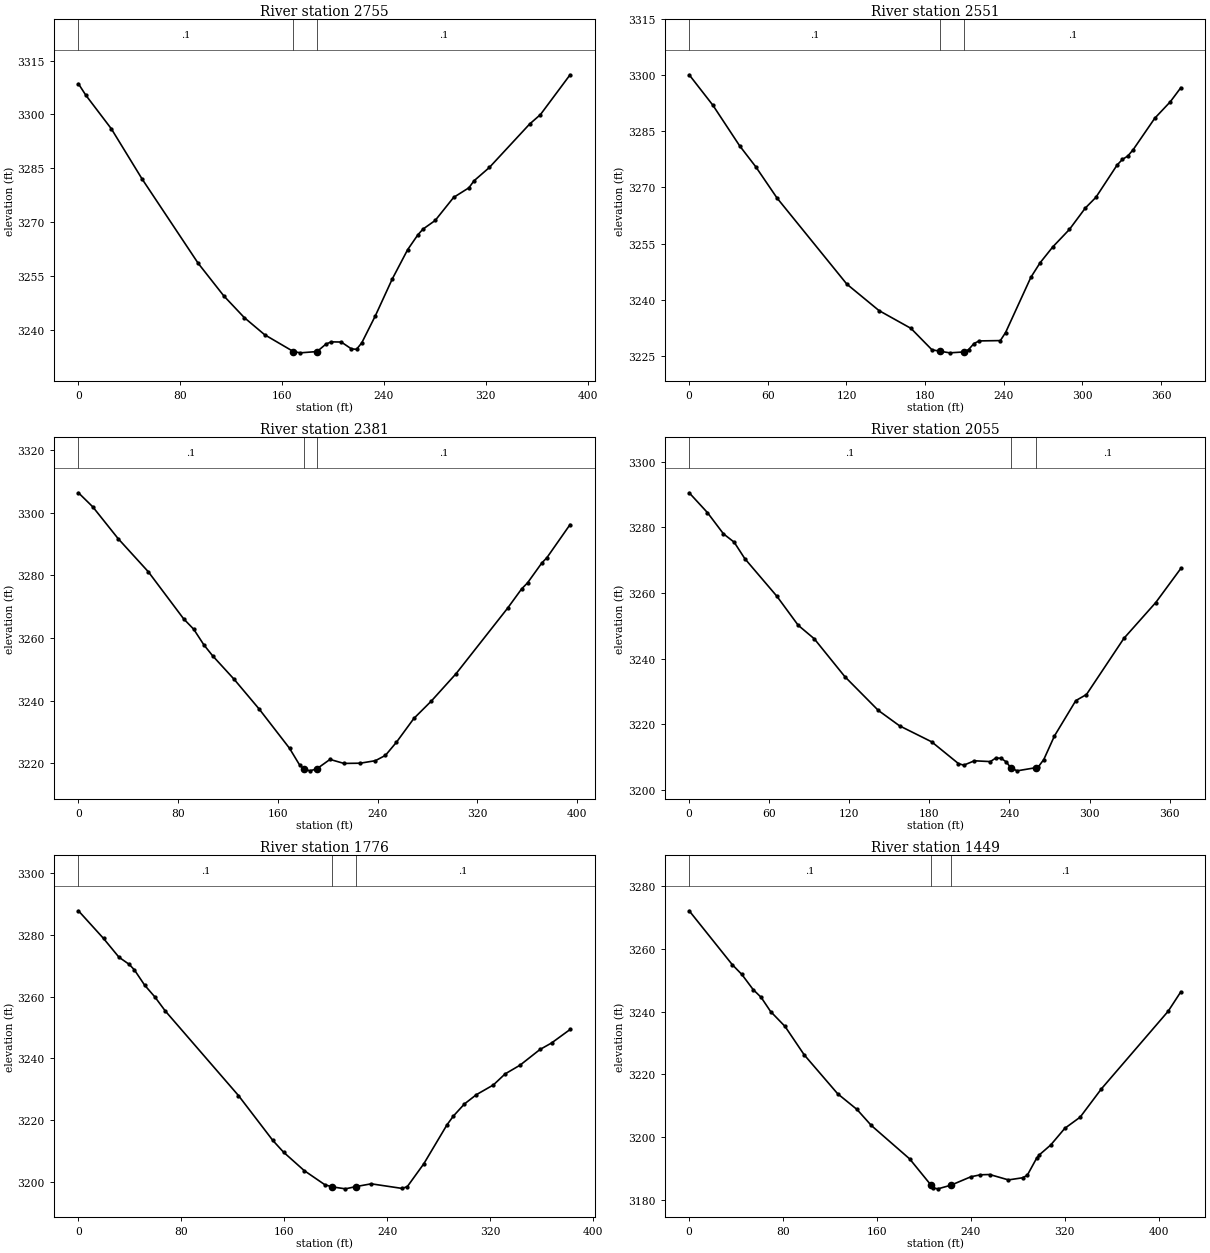
Type RM Length L Ch R = 1 ,2755    ,204.9,204.5,206.1
XS GIS Cut Line= 2
2328934.00572922526344.9899609872328548.99000021526376.207452529
#Sta/Elev= 30
       0 3308.53     5.8 3305.35    25.9 3295.98      50 3282.05    94.1 3258.58
   114.2 3249.53   130.3 3243.49   146.3 3238.72   168.9 3234.04   174.4 3233.68
   187.5 3234.04   194.5 3236.12   198.6 3236.73   206.5 3236.69   214.5 3234.78
   218.5 3234.66   222.6 3236.45   233.3 3243.99   246.6 3254.24   258.7  3262.4
   266.7 3266.51   270.7 3268.09   280.3  3270.5   294.8 3276.92   306.8 3279.59
   310.8 3281.53   322.9 3285.25   354.5 3297.32     363 3299.95   386.3 3311.03
#Mann= 3 ,-1,0
       0      .1       0   168.9    .045       0   187.5      .1       0
Bank Sta=168.9,187.5
XS Rating Curve= 0 ,0
Exp/Cntr(USF)=0,0
Exp/Cntr=0.3,0.1

Type RM Length L Ch R = 1 ,2551    ,170.8,169.2,169.2
XS GIS Cut Line= 4
2328913.90062111526124.5176809992328752.26695329526158.261674997
2328690.98918771526160.6805341652328544.19121423526184.344352284
#Sta/Elev= 30
       0 3300.17    18.1 3292.01    38.5 3281.15    50.8 3275.54    67.1 3267.14
   120.3 3244.12   144.8 3237.05   169.2 3232.28   185.2 3226.55   191.2 3226.17
   198.8 3225.73   209.93225.977   213.2 3226.62   217.3 3228.23   221.3 3228.92
   237.4 3229.01   241.4 3231.17   260.7 3245.96   267.7 3249.83   277.5 3254.13
   290.1 3258.77   302.2 3264.48   310.3 3267.36   326.5 3276.02   330.5 3277.51
   334.6 3278.41   338.7  3280.1   355.2 3288.53   367.1 3292.96   375.1 3296.72
#Mann= 3 ,-1,0
       0      .1       0   191.2    .045       0   209.9      .1       0
Bank Sta=191.2,209.9
XS Rating Curve= 0 ,0
Exp/Cntr(USF)=0,0
Exp/Cntr=0.3,0.1

Type RM Length L Ch R = 1 ,2381    ,324.3,325.9,329.8
XS GIS Cut Line= 2
2328907.58236821525961.7058736232328517.78761243526021.673801071
#Sta/Elev= 30
       0 3306.38    11.5 3301.89    31.8 3291.75    56.1 3281.12    84.4  3266.1
    92.5 3262.77   100.6  3257.8   107.7 3254.27   124.9 3246.78   145.1 3237.22
   169.4  3224.7   177.5 3219.35   180.7 3218.22   185.6 3217.53   191.2 3218.16
   201.8 3221.18     213  3219.9     226 3219.97   238.2 3220.77   246.3 3222.48
   255.1 3226.67   269.1 3234.28   283.1 3239.83   302.9 3248.56   344.3 3269.52
   355.5 3275.65   360.3 3277.61   371.7 3283.94   375.8 3285.64   394.4 3296.23
#Mann= 3 ,-1,0
       0      .1       0   180.7    .045       0   191.2      .1       0
Bank Sta=180.7,191.2
XS Rating Curve= 0 ,0
Exp/Cntr(USF)=0,0
Exp/Cntr=0.3,0.1

Type RM Length L Ch R = 1 ,2055    ,279.8,279.3,278.9
XS GIS Cut Line= 2
2328881.82612826525677.6868150852328513.52246898525685.428934049
#Sta/Elev= 30
       0 3290.51    13.7 3284.46    25.7 3277.99    33.7 3275.46    41.7 3270.43
    65.7 3258.99    81.7 3250.13    93.7 3246.03   116.6  3234.5   141.7  3224.2
   157.7 3219.48   181.7 3214.62   201.7 3208.01   205.7  3207.5   213.7 3208.84
   225.7  3208.6   229.7 3209.68   233.7 3209.62   237.7 3208.46  240.87 3206.76
   245.7 3205.78   259.7 3206.74   261.7 3207.05   265.7 3209.22   273.7 3216.41
   289.7 3227.18   297.7 3229.04   325.7 3246.13   349.6 3257.06   368.4 3267.45
#Mann= 3 ,-1,0
       0      .1       0  240.87    .045       0   259.7      .1       0
Bank Sta=240.87,259.7
XS Rating Curve= 0 ,0
Exp/Cntr(USF)=0,0
Exp/Cntr=0.3,0.1

Type RM Length L Ch R = 1 ,1776    ,326.3,327,326.5
XS GIS Cut Line= 4
 2328867.6536794525403.9840743812328723.60919432525404.358999951
2328606.26020187525411.2879592032328499.39991301525467.242315248
#Sta/Elev= 30
       0  3287.7    19.5 3278.76    31.5  3272.7    39.5 3270.38    43.5  3268.6
    51.5 3263.65    59.5 3259.82    67.5 3255.33   124.4    3228   151.1  3213.5
   159.5 3209.68   175.5 3203.75   191.6 3199.17   197.3 3198.48   207.6 3197.85
   215.6 3198.57   227.6 3199.47   251.7 3197.98   255.7 3198.59   268.5 3205.96
   286.5 3218.53   291.5 3221.38   300.1 3225.29   309.4 3228.29   322.6 3231.43
   331.7 3234.99   343.3 3237.81   358.8 3242.88   367.8 3244.98   382.2 3249.34
#Mann= 3 ,-1,0
       0      .1       0   197.3    .045       0   215.6      .1       0
Bank Sta=197.3,215.6
XS Rating Curve= 0 ,0
Exp/Cntr(USF)=0,0
Exp/Cntr=0.3,0.1

Type RM Length L Ch R = 1 ,1449    ,304.8,307.1,309.5
XS GIS Cut Line= 3
2328864.12985635525125.7658429522328677.86980912  525086.7723254
2328449.37348328525097.027892796
#Sta/Elev= 30
       0 3272.18    36.7    3255    44.9 3251.86    54.5 3247.05    61.3 3244.57
    69.4 3240.04    81.7 3235.28      98 3226.23   126.6 3213.78     143  3208.8
   155.2 3203.69   187.9 3193.02   206.3 3184.56     208 3183.76     212 3183.47
   223.1 3184.64     240 3187.31   248.2 3187.95   256.1 3188.04   272.1 3186.32
   284.1    3187   288.1 3187.78   296.1 3193.24   298.5 3194.34   308.1 3197.46
   320.1 3202.77   333.2 3206.34   351.3 3215.37   408.2 3240.13     419 3246.33
#Mann= 3 ,-1,0
       0      .1       0   206.3    .045       0   223.1      .1       0
Bank Sta=206.3,223.1
XS Rating Curve= 0 ,0
Exp/Cntr(USF)=0,0
Exp/Cntr=0.3,0.1

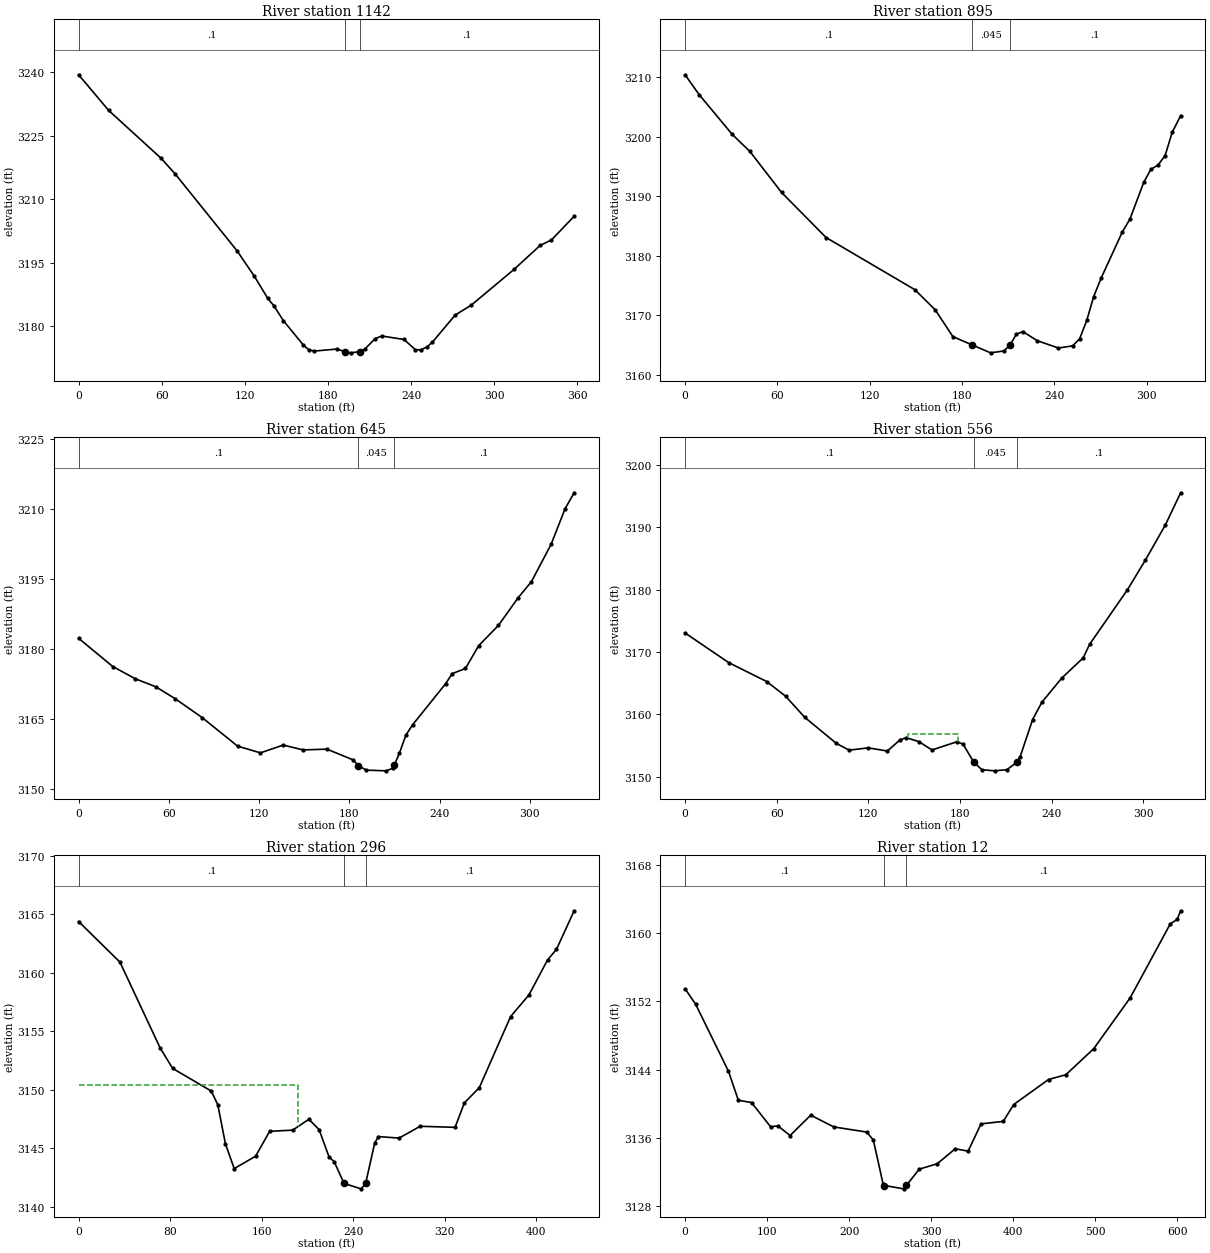
Type RM Length L Ch R = 1 ,1142    ,245.1,246.7,248.3
XS GIS Cut Line= 4
2328871.68810433524858.5181191982328732.84738362524793.131929534
 2328657.1576347524782.1307598662328532.09099403524808.472943521
#Sta/Elev= 30
       0 3239.44    21.7 3231.01    59.5 3219.72    69.8 3215.97   114.4 3197.83
   126.9 3191.81   136.5 3186.62   140.9 3184.88   147.9 3181.29   162.2 3175.59
   166.3 3174.41   170.3 3174.14   186.5 3174.62   192.2    3174   196.4 3173.72
  203.27 3174.02   206.7 3174.64     214 3177.04   218.8  3177.7     235 3176.88
   243.2 3174.42   247.3 3174.46   251.4 3175.09   255.5 3176.26   271.8 3182.62
   283.6 3185.02   314.4 3193.45   333.2  3199.1   341.4  3200.4   357.8    3206
#Mann= 3 ,-1,0
       0      .1       0   192.2    .045       0  203.27      .1       0
Bank Sta=192.2,203.27
XS Rating Curve= 0 ,0
Exp/Cntr(USF)=0,0
Exp/Cntr=0.3,0.1

Type RM Length L Ch R = 1 ,895     ,246.1,249.9,251.9
XS GIS Cut Line= 3
2328913.04034707524593.3605060982328701.01688916524540.603495444
2328611.42951257524488.841900086
#Sta/Elev= 30
       0 3210.36     9.1 3207.04    30.6 3200.37    42.1  3197.5    62.7 3190.62
    91.6 3183.07   149.3 3174.32   162.6 3170.92     174 3166.45   186.4 3165.07
   198.5 3163.73     207 3164.04   211.1 3164.98   215.2 3166.85   219.5  3167.3
   228.7 3165.78   242.6 3164.54   251.8  3164.9   256.4  3166.1     261 3169.17
   265.5 3173.17   270.3 3176.24   284.1    3184     289 3186.13     298  3192.3
   302.6 3194.49   307.2  3195.2   311.9  3196.8   316.5  3200.7     322 3203.51
#Mann= 3 ,-1,0
       0      .1       0   186.4    .045       0   211.1      .1       0
Bank Sta=186.4,211.1
XS Rating Curve= 0 ,0
Exp/Cntr(USF)=0,0
Exp/Cntr=0.3,0.1

Type RM Length L Ch R = 1 ,645     ,93,89.5,86.5
XS GIS Cut Line= 2
2328954.67060563524394.507529504 2328654.2359173524259.187222465
#Sta/Elev= 30
       0 3182.19    22.7 3176.14    37.8  3173.5    51.3 3171.81    64.2 3169.24
    82.2 3165.19   105.7 3159.08   120.9 3157.64     136 3159.31   149.3 3158.27
   165.1 3158.44   182.6 3156.13   185.9  3154.9   191.4 3153.94   204.5 3153.79
   208.9 3154.35   209.9 3155.04   213.3 3157.57   217.6 3161.45   222.1 3163.67
     244 3172.45   248.4 3174.62   257.2 3175.72     266 3180.61   279.1 3184.94
   292.3  3190.9   301.1 3194.34   314.2 3202.35   323.5 3209.99   329.5 3213.37
#Mann= 3 ,-1,0
       0      .1       0   185.9    .045       0   209.9      .1       0
Bank Sta=185.9,209.9
XS Rating Curve= 0 ,0
Exp/Cntr(USF)=0,0
Exp/Cntr=0.3,0.1

Type RM Length L Ch R = 1 ,556     ,252,260.1,278.2
XS GIS Cut Line= 3
 2329003.4879977524285.2114185862328867.44790733524246.500823767
2328690.48518816524200.048109984
#Sta/Elev= 30
       0 3173.04    28.6 3168.29    53.4 3165.27    65.8 3162.92    78.3 3159.54
    99.1 3155.35   107.4 3154.28   119.9 3154.65   132.4 3154.14   140.7 3155.93
   144.8 3156.28   153.1 3155.64   161.6 3154.31     178 3155.63     182 3155.24
     189 3152.34   194.3 3151.15   202.7 3150.97   210.7 3151.16   217.1 3152.33
   219.3  3153.2   227.5 3159.18   233.6 3161.97   246.7 3165.85   260.6 3169.05
   264.8 3171.22   289.6 3179.97   301.2 3184.66   314.4 3190.34   324.4 3195.49
#Mann= 3 ,-1,0
       0      .1       0     189    .045       0   217.1      .1       0
#XS Ineff= 1 ,-1
  146.09  178.35 3156.91
Permanent Ineff=
       F
Bank Sta=189,217.1
XS Rating Curve= 0 ,0
Exp/Cntr(USF)=0,0
Exp/Cntr=0.3,0.1

Type RM Length L Ch R = 1 ,296     ,274.9,283.2,274.9
XS GIS Cut Line= 4
2329062.10689842524197.8360759942328943.76307998524042.993696717
2328897.31036619523944.5581841762328769.01239479523926.861912259
#Sta/Elev= 30
       0 3164.38    36.1 3160.91    71.3 3153.56    82.2 3151.82     116 3149.88
   121.7  3148.7   128.3 3145.38     136 3143.25   154.7 3144.31     167 3146.44
   187.1 3146.54   201.3 3147.47   210.2 3146.59     219 3144.23   223.4 3143.85
     232 3141.98     247 3141.52   250.93141.978   258.8 3145.43   262.1 3145.99
   280.1 3145.86   298.6 3146.87   329.1 3146.78   337.2 3148.87   350.3 3150.18
   377.6 3156.25   393.7 3158.11   409.9 3161.09   417.7    3162   433.2  3165.3
#Mann= 3 ,-1,0
       0      .1       0     232    .045       0   250.9      .1       0
#XS Ineff= 2 , 0
          191.55 3150.38
Permanent Ineff=
       F       F
Bank Sta=232,250.9
XS Rating Curve= 0 ,0
Exp/Cntr(USF)=0,0
Exp/Cntr=0.3,0.1

Type RM Length L Ch R = 1 ,12      ,,,
XS GIS Cut Line= 4
2329117.40774816524041.8876797222329097.47003769523796.508866427
2329058.39311539523772.0594966812328764.17833288523875.716588792
#Sta/Elev= 30
       0 3153.48    12.8 3151.68    52.9 3143.81    64.9 3140.41      81 3140.14
   104.3 3137.29   113.1 3137.41     128 3136.27   153.2 3138.66   181.3 3137.28
   221.4 3136.68   229.5 3135.75   241.5 3130.55   243.1 3130.41   266.6 3130.02
   269.9 3130.43   285.5 3132.33   307.4 3132.96   329.4 3134.72   345.1 3134.44
   360.8 3137.64   387.9 3137.93   400.7 3139.91   443.1 3142.84   464.2  3143.4
   498.2 3146.45   542.7 3152.42   591.5 3161.08     600 3161.63   604.2 3162.63
#Mann= 3 ,0,0
       0      .1       0   243.1    .045       0   269.9      .1       0
Bank Sta=243.1,269.9
XS Rating Curve= 0 ,0
Exp/Cntr(USF)=0,0
Exp/Cntr=0.3,0.1
LCMann Table=0

Chan Stop Cuts=-1
Use User Specified Reach Order=0
Composite Channel Slope=5